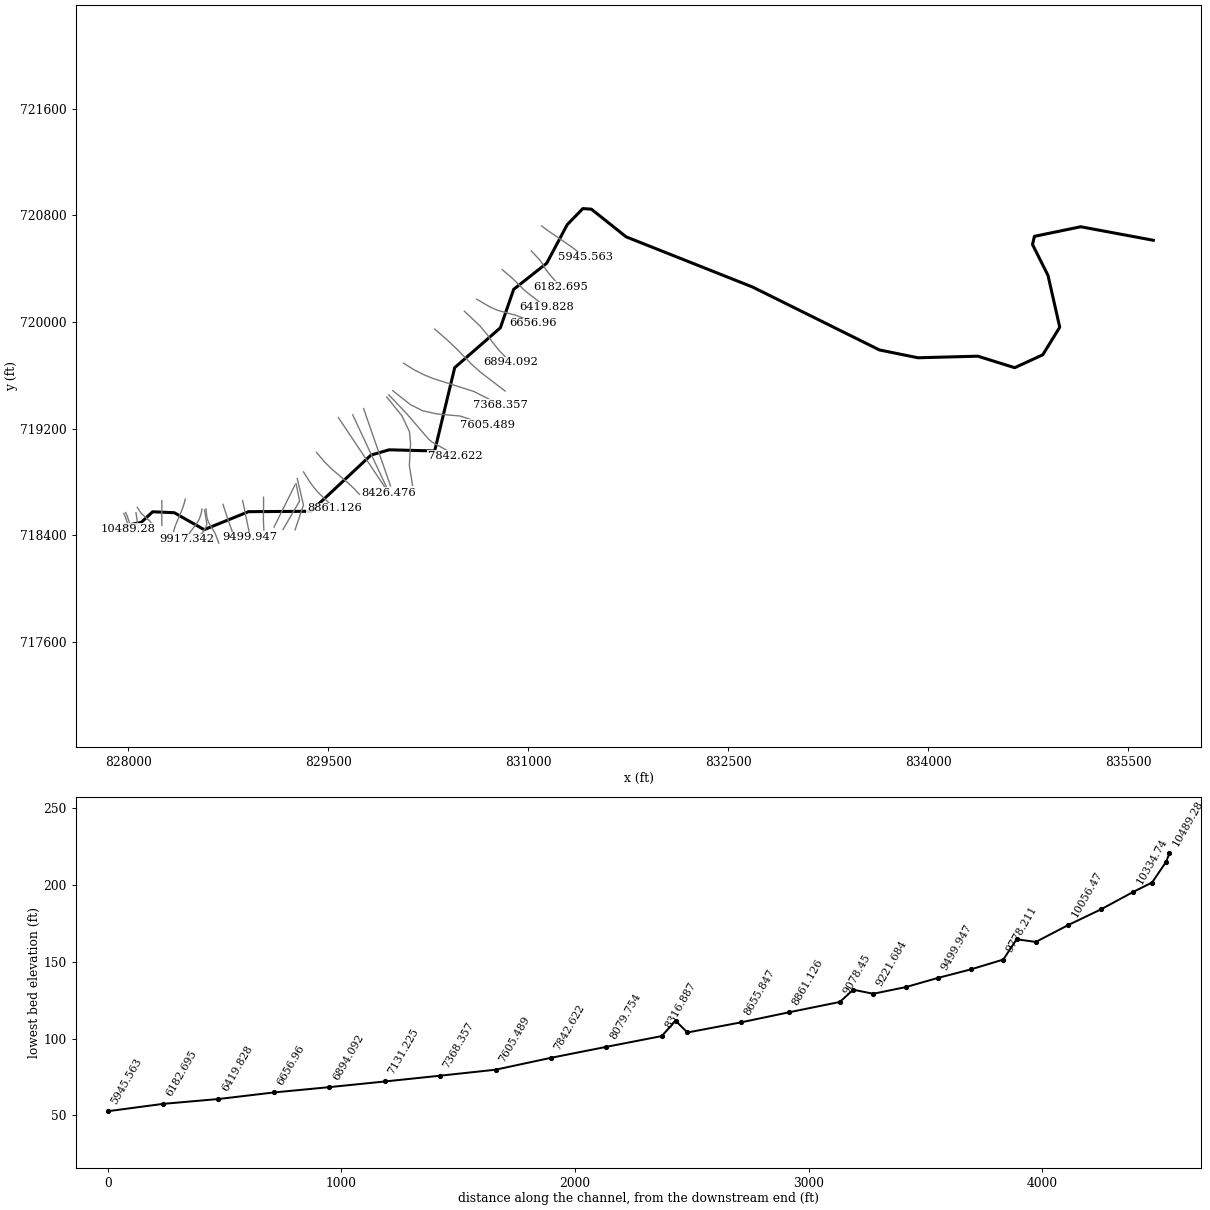
--- 7731_ras.prj (project) ---

Proj Title=7731
Current Plan=p01
Default Exp/Contr=0.3,0.1
English Units
Geom File=g01
Flow File=f01
Plan File=p01
Y Axis Title=Elevation
X Axis Title(PF)=Main Channel Distance
X Axis Title(XS)=Station
BEGIN DESCRIPTION:
RFD model 7731 exported to HEC-RAS
END DESCRIPTION:

--- 7731_ras.p01 (plan) ---

Plan Title=Plan 01
Program Version=4.10
Short Identifier=Plan 01
Geom File=g01
Flow File=f01
Subcritical Flow
Calc Critical at every XS
Secant Critical Depth

--- 7731_ras.f01 (steady flow) ---

Flow Title=Flow 01
Program Version=5.01
Number of Profiles= 6
Profile Names=10yr,25yr,50yr,100yr,100plus,500yr
River Rch & RM=7731,37,10489.28
  350.77  567.09  771.23  959.27 1400.54 2214.84
River Rch & RM=7731,37,10334.74
  352.38  569.73  774.86  963.83  1407.2 2224.08
River Rch & RM=7731,37,10195.61
  353.02  570.78  776.31  965.66 1409.86 2227.77
River Rch & RM=7731,37,10056.47
  359.74  581.83  791.52  984.75 1437.73 2266.38
River Rch & RM=7731,37,9917.342
  542.99  880.51 1200.31 1495.18 2182.96 3251.49
River Rch & RM=7731,37,9778.211
  545.62  884.84 1206.28 1502.68 2193.92 3265.79
River Rch & RM=7731,37,9639.079
  546.79  886.76 1208.93 1506.01 2198.78 3272.13
River Rch & RM=7731,37,9499.947
  549.41  891.08 1214.89  1513.5 2209.72  3286.4
River Rch & RM=7731,37,9360.816
  550.87  893.48  1218.2 1517.66 2215.79 3294.31
River Rch & RM=7731,37,9221.684
  748.68 1217.98 1664.35 2076.73 3032.03 4326.12
River Rch & RM=7731,37,9136.271
  750.53 1221.07 1668.63 2082.14 3039.92 4336.07
River Rch & RM=7731,37,8861.126
  756.33 1230.73 1682.03 2099.07 3064.64 4367.27
River Rch & RM=7731,37,8655.847
  758.18  1233.8 1686.29 2104.45  3072.5 4377.18
River Rch & RM=7731,37,8426.476
  813.03 1324.75 1812.23 2263.23 3304.32 4666.39
River Rch & RM=7731,37,8375.605
  819.35 1335.34    1827 2281.97 3331.68 4700.84
River Rch & RM=7731,37,8079.754
  832.96 1358.05 1858.55 2321.87 3389.93 4773.54
River Rch & RM=7731,37,7842.622
  833.48  1358.9 1859.74 2323.38 3392.13 4776.28
River Rch & RM=7731,37,7605.489
  837.57 1365.73 1869.23 2335.38 3409.66 4798.14
River Rch & RM=7731,37,7368.357
  839.53 1369.04 1873.86 2341.29 3418.28 4809.05
River Rch & RM=7731,37,7131.225
  850.61 1387.71 1899.99 2374.52  3466.8 4870.27
River Rch & RM=7731,37,6894.092
  855.24 1395.54 1910.94 2388.48 3487.18 4896.02
River Rch & RM=7731,37, 6656.96
  865.41 1412.74 1935.06 2419.22 3532.07 4952.77
River Rch & RM=7731,37,6419.828
  867.33 1415.99 1939.63 2425.05 3540.58 4963.55
River Rch & RM=7731,37,6182.695
  875.48  1429.8 1959.02  2449.8  3576.7 5009.26
River Rch & RM=7731,37,5945.563
   877.4 1433.05 1963.58 2455.61 3585.19 5019.99
River Rch & RM=7731,37,5858.732
  878.11 1434.26 1965.28 2457.79 3588.37 5024.01
River Rch & RM=7731,37,5769.965
  879.79  1437.1 1969.26 2462.87 3595.79 5033.39
Boundary for River Rch & Prof#=7731,37,1
Up Type= 0
Dn Type= 2
Boundary for River Rch & Prof#=7731,37,2
Up Type= 0
Dn Type= 2
Boundary for River Rch & Prof#=7731,37,2
Up Type= 0
Dn Type= 2
Boundary for River Rch & Prof#=7731,37,2
Up Type= 0
Dn Type= 2
Boundary for River Rch & Prof#=7731,37,2
Up Type= 0
Dn Type= 2
Boundary for River Rch & Prof#=7731,37,2
Up Type= 0
Dn Type= 2

--- 7731_ras.g01 (geometry) ---

Geom Title=7731
Program Version=4.10

River Reach=7731,37
Reach XY= 30
827987.537292182718475.537227377828098.214375556718498.106671825
828184.151875526718577.533755168828346.478264391718570.589310721
828570.436597764718443.419171825828903.037421405718578.429508224
829370.545104712 718581.21214059 829821.12513116719002.555248097
829957.489757031719042.303851649830298.822014391719033.577591956
830449.090387613719658.554156318830791.443542182719956.971689224
830891.269931108720245.600161418831138.665764391720440.912661448
831292.718509525720730.477382824831409.933125556720851.068911418
831473.952222735720846.728633627831734.710514367720639.010886222
  832682.4170959720262.972800389833634.478951007719790.880866885
833922.332892984719732.398164913834371.411543548719744.272947535
834648.152580947719657.989833817834858.655344635719754.703291669
834985.930795014719961.554283798834897.920256853720349.880986243
834781.626276851720581.955318362834796.193960905 720643.03793104
835143.354557902720714.787099183835687.427712083720613.481664911

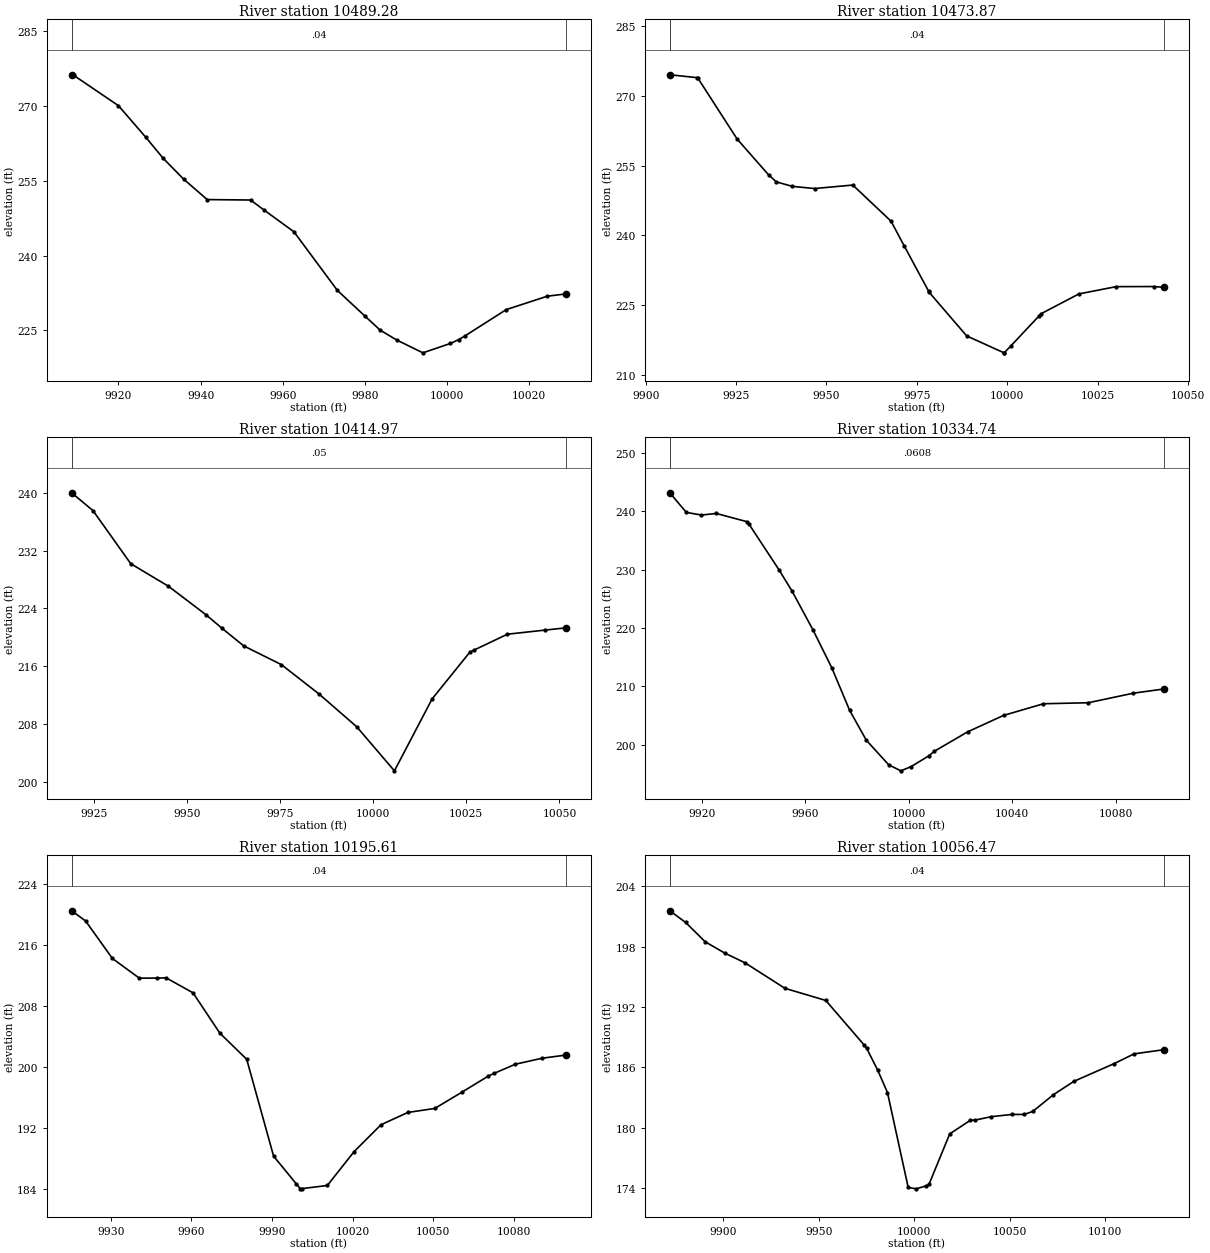
Type RM Length L Ch R = 1 ,10489.28,15.412800,15.412800,15.412800
XS GIS Cut Line= 6
827967.826197034718565.475284441827978.695894961718540.437279108
827992.994502351718498.563401057827998.405020996718478.503441732
827998.833212428718476.549816238827997.030045981  718450.5012305
#Sta/Elev= 21
9908.573276.28439909.091 276.1719919.993270.08969926.588263.81179930.894 259.526
9935.869255.35779941.614251.24879952.181251.16189955.377249.20849962.748244.7899
9973.315233.05089980.116227.81869983.807225.03029987.818 223.0699994.165 220.505
10000.89222.394810002.89223.163510004.45223.917110014.47229.176410024.49231.8716
   10029232.3211
#Mann= 3 , 0 , 0
9908.573    0.04       09908.573    0.04       0   10029    0.04       0
#XS Ineff= 2 , 0
       0                               0
Bank Sta=9908.573,10029
Exp/Cntr=0.3,0.1

Type RM Length L Ch R = 1 ,10473.87,58.897700,58.897700,58.897700
XS GIS Cut Line= 6
827982.012419232718572.080103877827992.882121605 718547.04210347
828007.180736885718505.168232886828012.591259445718485.108276837
828013.019451279718483.154651637828023.745379798718442.206330742
#Sta/Elev= 23
 9906.68274.47279914.182273.86269914.398273.8105  9925.3260.67739933.975253.0128
9936.133251.49729940.529 250.535  9946.7250.06959957.267250.81189967.834243.0714
9971.475237.76879978.223228.04849978.397 227.7929988.755218.4491    9999214.8471
9999.111214.8179   10001216.329810008.82 222.79210009.43223.252310019.77227.4565
 10030.1229.022310040.44229.041110043.33228.8737
#Mann= 3 , 0 , 0
 9906.68    0.04       0 9906.68    0.04       010043.33    0.04       0
#XS Ineff= 2 , 0
       0                               0
Bank Sta=9906.68,10043.33
Exp/Cntr=0.3,0.1

Type RM Length L Ch R = 1 ,10414.97,80.233900,80.233900,80.233900
XS GIS Cut Line= 2
 828059.00508277718570.699103551828078.669701459718439.481857341
#Sta/Elev= 17
 9919.05239.97359924.813237.50579934.924230.18399945.036227.06979955.148223.1214
9959.499221.23129965.259218.82699975.371216.23929985.483212.17899995.594207.6569
10005.71201.571510015.82 211.49810025.93217.945110026.97 218.22210036.04220.4413
10046.15221.009710051.73221.3188
#Mann= 3 , 0 , 0
 9919.05    0.05       0 9919.05    0.05       010051.73    0.05       0
#XS Ineff= 2 , 0
       0                               0
Bank Sta=9919.05,10051.73
Exp/Cntr=0.3,0.1

Type RM Length L Ch R = 1 ,10334.74,139.131700,139.131700,139.131700
XS GIS Cut Line= 6
828069.229828095 718610.62139151828088.837657605718578.523066716
828103.774350596718560.678860724828161.245583816718509.672997694
828176.930779266718487.470185899828188.620181006718464.341681625
#Sta/Elev= 23
9907.723243.20789914.098239.84219919.953239.38539925.653239.6617 9937.62238.2367
9938.386237.78019949.966229.94729954.972226.31769963.007219.69619970.279213.1921
9977.211 205.8529983.633200.7465  9992.3196.51659996.986195.4887   10001196.2297
10007.79198.065510009.95198.854210022.78202.181210036.66205.001710052.06207.0017
 10069.4 207.17510086.79208.815210098.67209.5405
#Mann= 3 , 0 , 0
9907.723  0.0608       09907.723  0.0608       010098.67  0.0608       0
#XS Ineff= 2 , 0
       0                               0
Bank Sta=9907.723,10098.67
Exp/Cntr=0.3,0.1

Type RM Length L Ch R = 1 ,10195.61,139.131600,139.131600,139.131600
XS GIS Cut Line= 6
828252.473378084718660.198731107828253.520887678718628.575168862
828252.776182142 718576.60359554828252.683688611718574.605735429
828252.451440042718502.828936816 828254.08076298718476.220408164
#Sta/Elev= 24
9915.382 220.4629920.584219.13669930.589214.21749940.595211.64289947.023211.6456
9950.599 211.679  9960.6209.71979970.601204.43729980.602201.01419990.603188.3426
    9999184.731510000.61184.0562   10001184.078610010.61184.495510020.61188.9395
10030.61192.449410040.61194.058710050.61194.580910060.61196.683910070.61 198.833
10072.78199.183210080.62200.372310090.64201.159910099.44201.5699
#Mann= 3 , 0 , 0
9915.382    0.04       09915.382    0.04       010099.44    0.04       0
#XS Ineff= 2 , 0
       0                               0
Bank Sta=9915.382,10099.44
Exp/Cntr=0.3,0.1

Type RM Length L Ch R = 1 ,10056.47,139.131600,139.131600,139.131600
XS GIS Cut Line= 6
828428.560593906 718673.07428665828422.928909927718648.437546713
828411.592868338718612.263556542 828397.72649032718576.094465875
828356.216614318718478.431926128828340.646908309718430.073310236
#Sta/Elev= 27
9871.929201.55329880.212200.3949 9890.47198.47079900.804197.33779911.283196.3857
9932.243193.84579953.599192.64319973.846188.18489975.035187.87969980.817185.7034
9985.901183.49239996.767174.0565   10001173.918710006.27174.222610007.65174.3654
10018.52179.381810029.38180.740810031.87 180.75210040.24181.0907 10051.1181.3114
10057.48181.314110061.97181.608910072.83183.277310083.57184.605710104.58186.3609
10115.09187.333910130.77  187.75
#Mann= 3 , 0 , 0
9871.929    0.04       09871.929    0.04       010130.77    0.04       0
#XS Ineff= 2 , 0
       0                               0
Bank Sta=9871.929,10130.77
Exp/Cntr=0.3,0.1

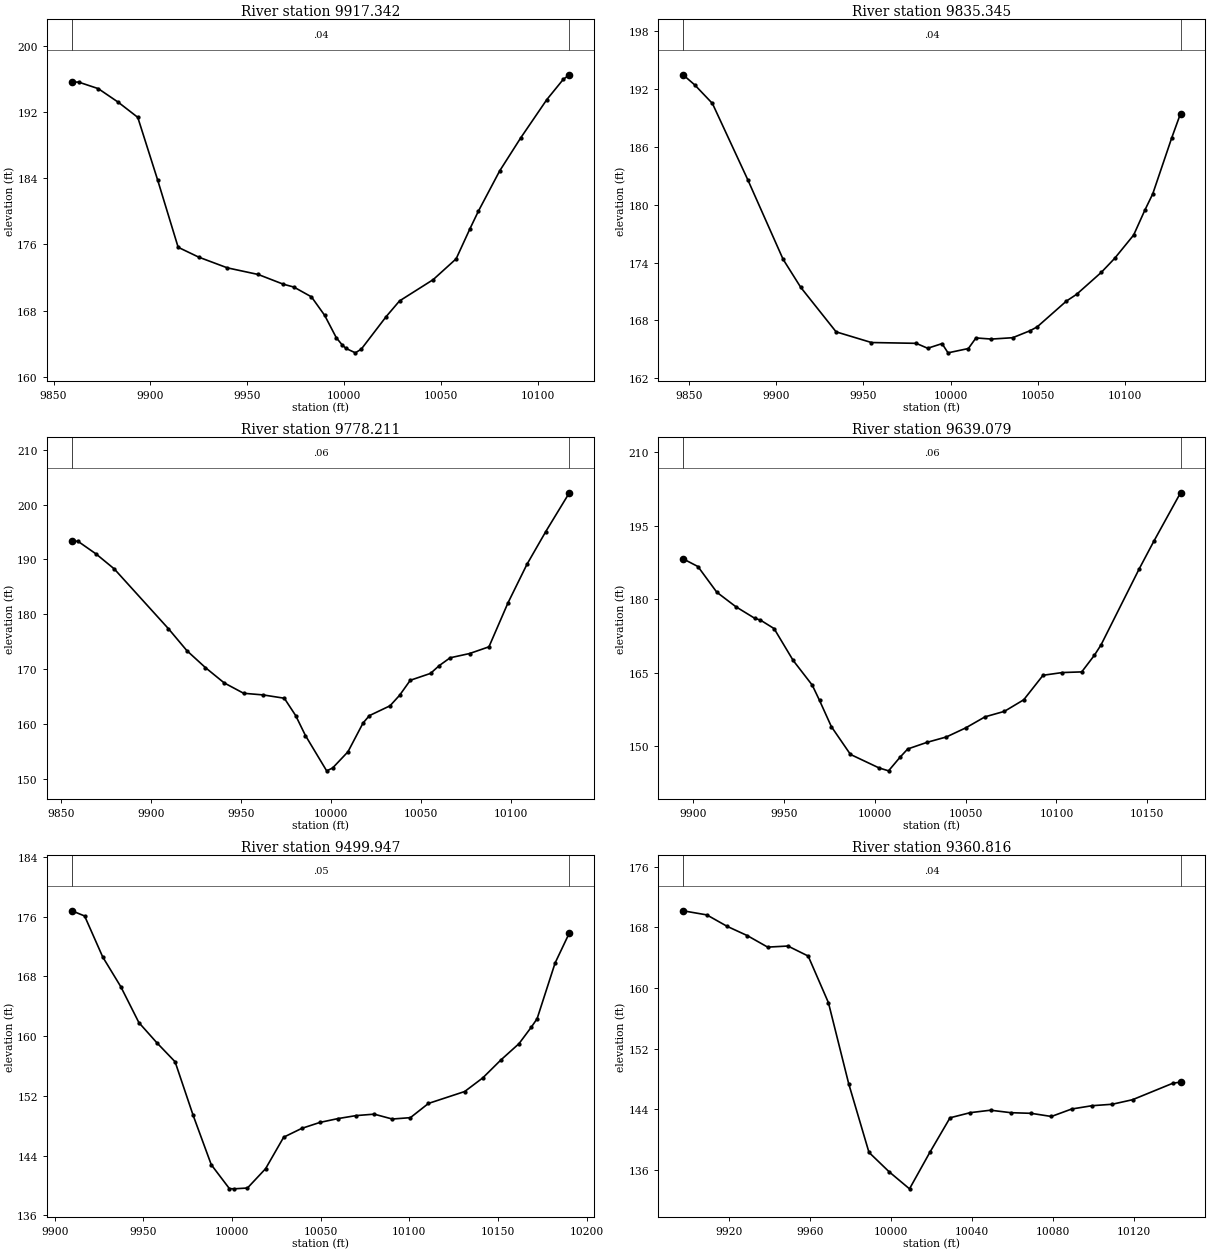
Type RM Length L Ch R = 1 ,9917.342,81.996700,81.996700,81.996700
XS GIS Cut Line= 6
828554.118155567718598.364692591828545.531112084718555.128892257
828533.100766863718521.154885862 828518.43496814718496.308253077
828461.187098964718418.953874709828440.548309087718372.042595283
#Sta/Elev= 30
9859.456195.58729862.886195.59339873.081194.80099883.277193.18189893.472191.3359
9903.673183.81859914.321 175.652 9924.97174.46029939.712173.17079955.649172.3694
9968.564171.19969974.029170.85149983.104169.67199989.939167.43499995.961164.7303
    9999 163.863   10001163.438710005.78 162.91310008.86 163.36710021.71167.2958
10028.58169.180310045.94171.748410057.78174.257410064.95177.906610069.28180.0161
10080.23184.861110091.19 188.884 10104.6193.4808 10113.1195.926710116.22196.4726
#Mann= 3 , 0 , 0
9859.456    0.04       09859.456    0.04       010116.22    0.04       0
#XS Ineff= 2 , 0
       0                10037.46       0
Bank Sta=9859.456,10116.22
Exp/Cntr=0.3,0.1

Type RM Length L Ch R = 1 ,9835.345,57.134900,57.134900,57.134900
XS GIS Cut Line= 6
828573.349971953718591.626148113828590.487469828718484.310069623
828582.623731354718460.649281291828560.426870284718423.652432262
 828530.28482797 718393.03641191828470.401450613718366.772250311
#Sta/Elev= 27
9846.653193.47029853.363192.4195 9863.49190.49589883.743182.59039903.997 174.336
9914.123 171.4229934.377166.8111 9954.63165.70459980.262165.6212 9986.85165.1102
9995.081165.59219998.512164.635310010.17165.082610014.52166.180710023.41166.0624
10035.55166.2041 10045.4166.919810049.58167.322510066.37170.005910072.14 170.695
10086.38172.985110093.98174.4285 10104.9176.853310111.28179.421410115.82181.1147
10126.74186.944410131.76189.4538
#Mann= 3 , 0 , 0
9846.653    0.04       09846.653    0.04       010131.76    0.04       0
#XS Ineff= 2 , 0
       09968.378        10021.02       0
Bank Sta=9846.653,10131.76
Exp/Cntr=0.3,0.1

Type RM Length L Ch R = 1 ,9778.211,139.131600,139.131600,139.131600
XS GIS Cut Line= 6
828584.002946489 718598.44567144828589.795920985718542.545954455
828596.682994121718515.905631295828605.337922234718495.163541343
828654.266070634718412.410605842828679.325308291718342.519997856
#Sta/Elev= 30
9855.994193.40899859.442193.29199869.501190.98389879.559188.27189909.733177.3549
9919.996173.34949930.324170.25769940.699167.48329951.535165.58669962.386165.2858
 9974.16164.68279980.494161.51229985.935 157.868 9997.71 151.442   10001151.9533
10009.56154.916910017.96160.166210021.46161.508210032.96163.303610038.28165.2203
10044.22167.956710055.49169.211910060.36170.6408 10066.4 172.05910077.19172.8332
10087.98174.058110098.59182.0919 10109.1 189.091 10119.6195.0847 10132.7202.1497
#Mann= 3 , 0 , 0
9855.994    0.06       09855.994    0.06       0 10132.7    0.06       0
#XS Ineff= 2 , 0
       0                               0
Bank Sta=9855.994,10132.7
Exp/Cntr=0.3,0.1

Type RM Length L Ch R = 1 ,9639.079,139.131700,139.131700,139.131700
XS GIS Cut Line= 6
828712.657508431718632.893559345828717.355086578718615.906996967
828744.020971041718533.232442175828748.428270644718518.986106634
828787.087285841718412.663689349828799.399802837718373.293786576
#Sta/Elev= 30
9894.507 188.3019902.697186.72679913.084181.48299923.592 178.5189934.099176.1336
9937.036175.80849944.606174.06349955.114167.55969965.621162.51769969.613159.4107
9976.128154.05799986.635148.382510002.37 145.62610007.61145.030810013.91147.8003
10018.15149.490510028.79150.848110039.44151.946410050.08153.796310060.72156.0555
10071.36157.1701   10082159.530110092.64164.535710103.28  165.0910113.92165.2235
10120.94168.643210124.56170.744310145.55186.251610153.55191.8514 10168.3201.7756
#Mann= 3 , 0 , 0
9894.507    0.06       09894.507    0.06       0 10168.3    0.06       0
#XS Ineff= 2 , 0
       0                               0
Bank Sta=9894.507,10168.3
Exp/Cntr=0.3,0.1

Type RM Length L Ch R = 1 ,9499.947,139.131600,139.131600,139.131600
XS GIS Cut Line= 6
828858.848358028718662.059232302828859.300078625718659.592517161
828876.820863452718574.507824681 828877.19115477718572.542402532
828911.251948702718408.294841878828915.262575164718387.105055231
#Sta/Elev= 30
9909.622176.77589916.819176.07969927.029170.59689937.239166.61079947.448161.8029
9957.658159.08789967.868156.56169978.078149.37579988.288142.77719998.497139.5863
   10001139.5516 10008.7139.661610018.92142.247110029.13146.465410039.34147.6465
10049.55148.441910059.77148.956410069.98149.356210080.19149.5499 10090.4148.8967
10100.62149.080710110.83 150.98710131.26152.580310141.47154.406510151.68156.8048
10161.89158.984810168.74161.1644 10172.1162.317110182.27169.789210190.31173.8064
#Mann= 3 , 0 , 0
9909.622    0.05       09909.622    0.05       010190.31    0.05       0
#XS Ineff= 2 , 0
       0                               0
Bank Sta=9909.622,10190.31
Exp/Cntr=0.3,0.1

Type RM Length L Ch R = 1 ,9360.816,139.131600,139.131600,139.131600
XS GIS Cut Line= 6
829015.340448856718686.739011123829016.083686862718672.085142423
829015.440210263718585.235229102829015.327109464718583.238429621
 829014.27540402718517.987737076829018.024789338718441.341704143
#Sta/Elev= 25
9897.475170.16469909.229169.61939919.233168.11459929.233166.88729939.234165.3763
9949.234165.51829959.234   164.29969.234158.04779979.235147.37179989.235138.3253
9999.236135.755510009.24133.519910019.24 138.31110029.24142.882710039.24143.5601
10049.24143.883110059.25143.555310069.25143.472310079.26143.056510089.27144.0396
10099.29144.4752 10109.3144.667710119.31145.265110139.33147.4509   10143147.5763
#Mann= 3 , 0 , 0
9897.475    0.04       09897.475    0.04       0   10143    0.04       0
#XS Ineff= 2 , 0
       0                               0
Bank Sta=9897.475,10143
Exp/Cntr=0.3,0.1

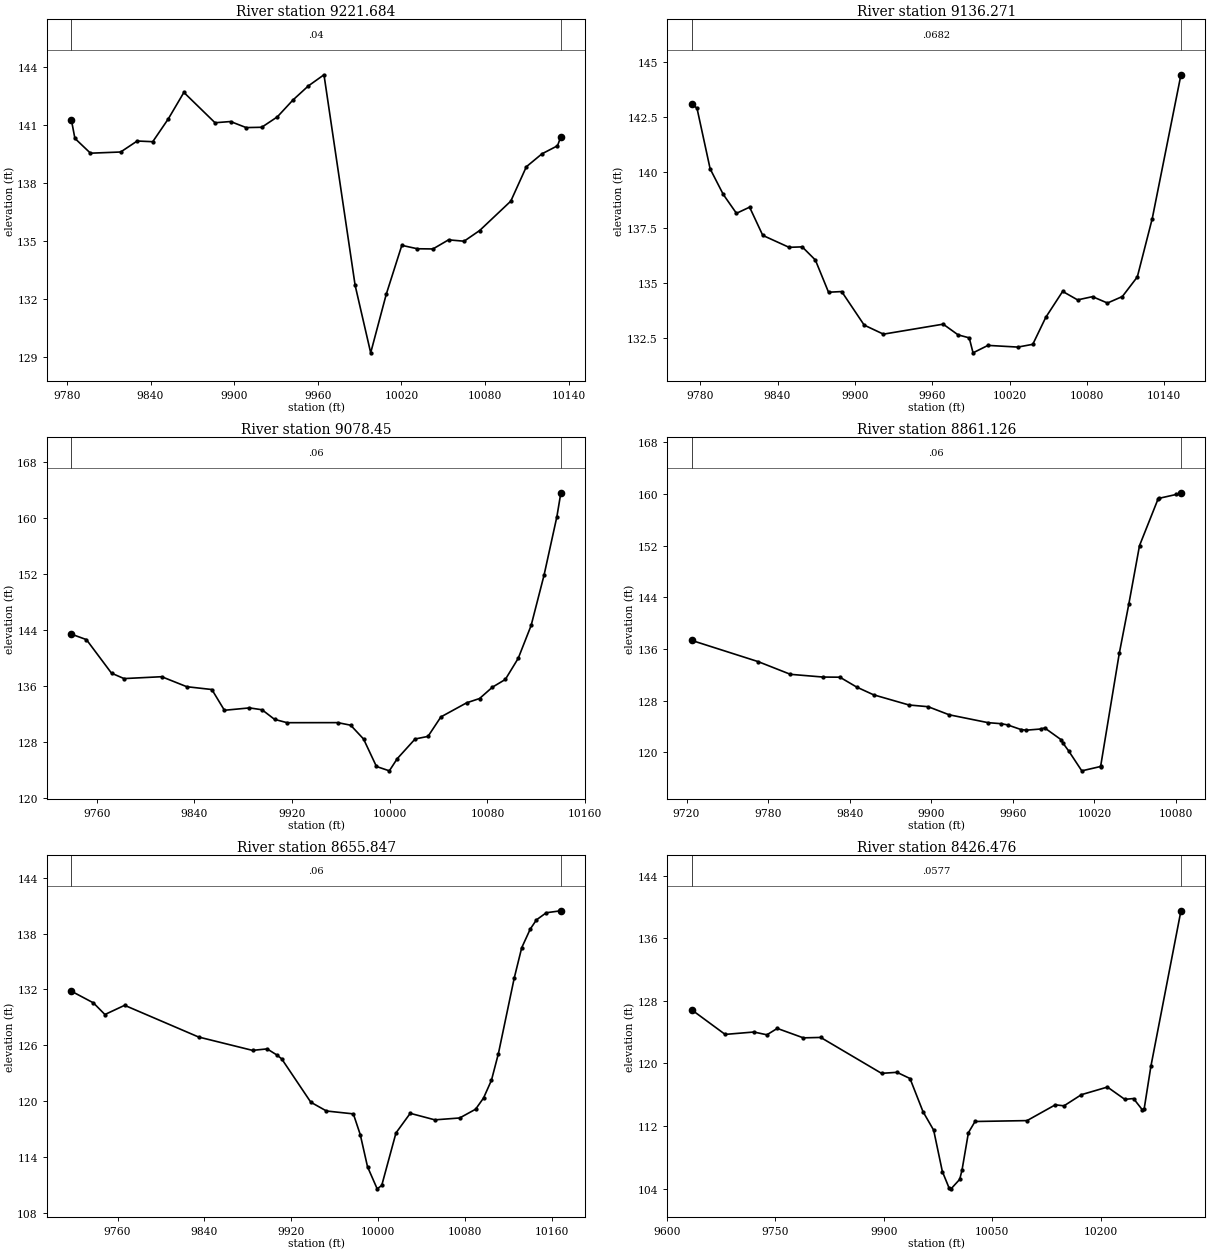
Type RM Length L Ch R = 1 ,9221.684,85.413600,85.413600,85.413600
XS GIS Cut Line= 2
829250.737660259718777.223146652829094.274450608718462.836582496
#Sta/Elev= 30
 9783.24141.23189785.724140.29389796.894139.52829818.562139.59039830.404140.1588
9841.574140.12339852.744141.30679863.914142.67559886.254 141.1059897.423141.1678
9908.593 140.8549919.763140.87029930.933141.40739942.103142.27679953.228143.0127
9964.443143.58889986.783132.68649997.953129.189810009.12132.223410020.29 134.756
10031.46134.579310042.63134.5699 10053.8135.040610064.97134.970810076.14135.5239
10098.48137.045210109.65138.826610120.82139.493910131.99139.912410134.41140.3867
#Mann= 3 , 0 , 0
 9783.24    0.04       0 9783.24    0.04       010134.41    0.04       0
#XS Ineff= 2 , 0
       0                10038.03       0
Bank Sta=9783.24,10134.41
Exp/Cntr=0.3,0.1

Type RM Length L Ch R = 1 ,9136.271,57.820300,57.820300,57.820300
XS GIS Cut Line= 3
829259.376271056718789.148411605829286.159483191718657.891354258
829162.037955862718445.783671449
#Sta/Elev= 30
9773.285  143.129777.519142.91679787.725140.16329797.931138.99999808.137138.1446
9818.343 138.4249828.549137.14369848.961136.60099859.167136.62219869.373136.0244
9879.579134.56339889.785134.59349907.247133.07129922.183132.66049968.528133.1139
9980.115132.62829988.741132.49269991.701131.812510003.29132.150610026.46132.0738
10038.05132.199410048.14133.424810061.22134.601210072.81134.215710084.39134.3623
10095.98134.072910107.54134.368410119.15135.256810130.74137.9077   10153144.4324
#Mann= 3 , 0 , 0
9773.285  0.0682       09773.285  0.0682       0   10153  0.0682       0
#XS Ineff= 2 , 0
       09968.197        10040.63       0
Bank Sta=9773.285,10153
Exp/Cntr=0.3,0.1

Type RM Length L Ch R = 1 , 9078.45,217.324700,217.324700,217.324700
XS GIS Cut Line= 3
829268.357438068718826.930150854829315.143253149718628.420954117
829252.062724005718441.924435729
#Sta/Elev= 30
9739.302143.39369751.559142.61699772.107 137.8179782.381137.04279813.203137.3106
9833.751135.88139854.299135.47829864.573132.50999885.121132.85039895.395132.5829
9905.669131.20779915.943130.73399957.418130.74329967.975130.37559978.531128.4029
9989.088124.47329999.644 123.84910006.12125.587710020.76128.405310031.31128.7732
10041.87131.560210062.98 133.57910073.54134.1908 10084.1135.816710094.65136.9199
10105.21139.942510115.77144.635710126.32151.803610136.88160.203710140.13163.6151
#Mann= 3 , 0 , 0
9739.302    0.06       09739.302    0.06       010140.13    0.06       0
#XS Ineff= 2 , 0
       09962.188        10036.85       0
Bank Sta=9739.302,10140.13
Exp/Cntr=0.3,0.1

Type RM Length L Ch R = 1 ,8861.126,205.278400,205.278400,205.278400
XS GIS Cut Line= 6
829315.210396276718876.439926091829362.851673591718801.129534314
829390.161206674718763.736117914829424.296045472718723.162415019
829520.083085405718630.815025362829546.011112699718602.554368111
#Sta/Elev= 30
9723.694137.33959772.693134.04579796.383132.08039820.402131.65599832.785131.6352
9845.168130.10219857.551128.90779883.601  127.339897.699127.06389913.146125.8137
9941.757124.59299951.523 124.4319956.062124.2472 9965.89123.53339969.787123.4292
9980.636123.61349983.393123.77859995.382121.9672    9997121.3751   10001120.2221
10010.67117.132410024.45117.8019 10024.6117.923410038.22135.310210045.23142.9356
10053.12 152.01610066.69159.197910067.29159.327110080.26159.941810083.58160.1942
#Mann= 3 , 0 , 0
9723.694    0.06       09723.694    0.06       010083.58    0.06       0
#XS Ineff= 2 , 0
       0                               0
Bank Sta=9723.694,10083.58
Exp/Cntr=0.3,0.1

Type RM Length L Ch R = 1 ,8655.847,229.371000,229.371000,229.371000
XS GIS Cut Line= 6
 829412.56220243719022.893387323829472.327507485718952.412575527
829522.235222719718902.506374842829652.271666303718790.622020739
829697.298784866718748.474991676829734.073125053718708.457717364
#Sta/Elev= 30
9717.526131.80489737.739130.55479748.342129.30359766.492130.29269834.599126.8879
9884.263125.45249897.683125.61249906.803124.94849911.103124.54069937.913119.8858
9952.347118.94269977.077118.6341 9983.46116.39739990.131112.95249999.013110.5841
10003.21110.949210016.33116.588710029.45118.694110052.11117.992510074.97 118.194
10089.61119.133310096.94120.335210104.24122.249110110.64125.113410125.17133.2037
10132.09136.473510139.95138.479410145.67139.469410154.73140.233510168.14140.4441
#Mann= 3 , 0 , 0
9717.526    0.06       09717.526    0.06       010168.14    0.06       0
#XS Ineff= 2 , 0
       09966.313        10027.64       0
Bank Sta=9717.526,10168.14
Exp/Cntr=0.3,0.1

Type RM Length L Ch R = 1 ,8426.476,50.870900,50.870900,50.870900
XS GIS Cut Line= 2
 829577.04502419 719283.67854243829953.294047968718720.399276054
#Sta/Elev= 30
9633.855126.86619680.369123.71139720.191124.01719738.195123.66089752.523124.4778
  9788.6123.27139812.651123.32529896.831118.7408 9918.23 118.8719936.234118.0785
9954.238113.84739968.985111.48239981.011106.20479990.245 104.1239993.037103.9939
10005.06105.209710008.25106.398310017.09111.166710026.25112.592110098.27112.7071
10137.35114.720910149.37114.591410173.42116.0143 10209.5116.989810233.55115.4178
10245.58115.5243 10257.6 114.108 10260.3114.181110269.63119.635610311.24139.4964
#Mann= 3 , 0 , 0
9633.855  0.0577       09633.855  0.0577       010311.24  0.0577       0
#XS Ineff= 2 , 0
       09954.484        10059.87       0
Bank Sta=9633.855,10311.24
Exp/Cntr=0.3,0.1

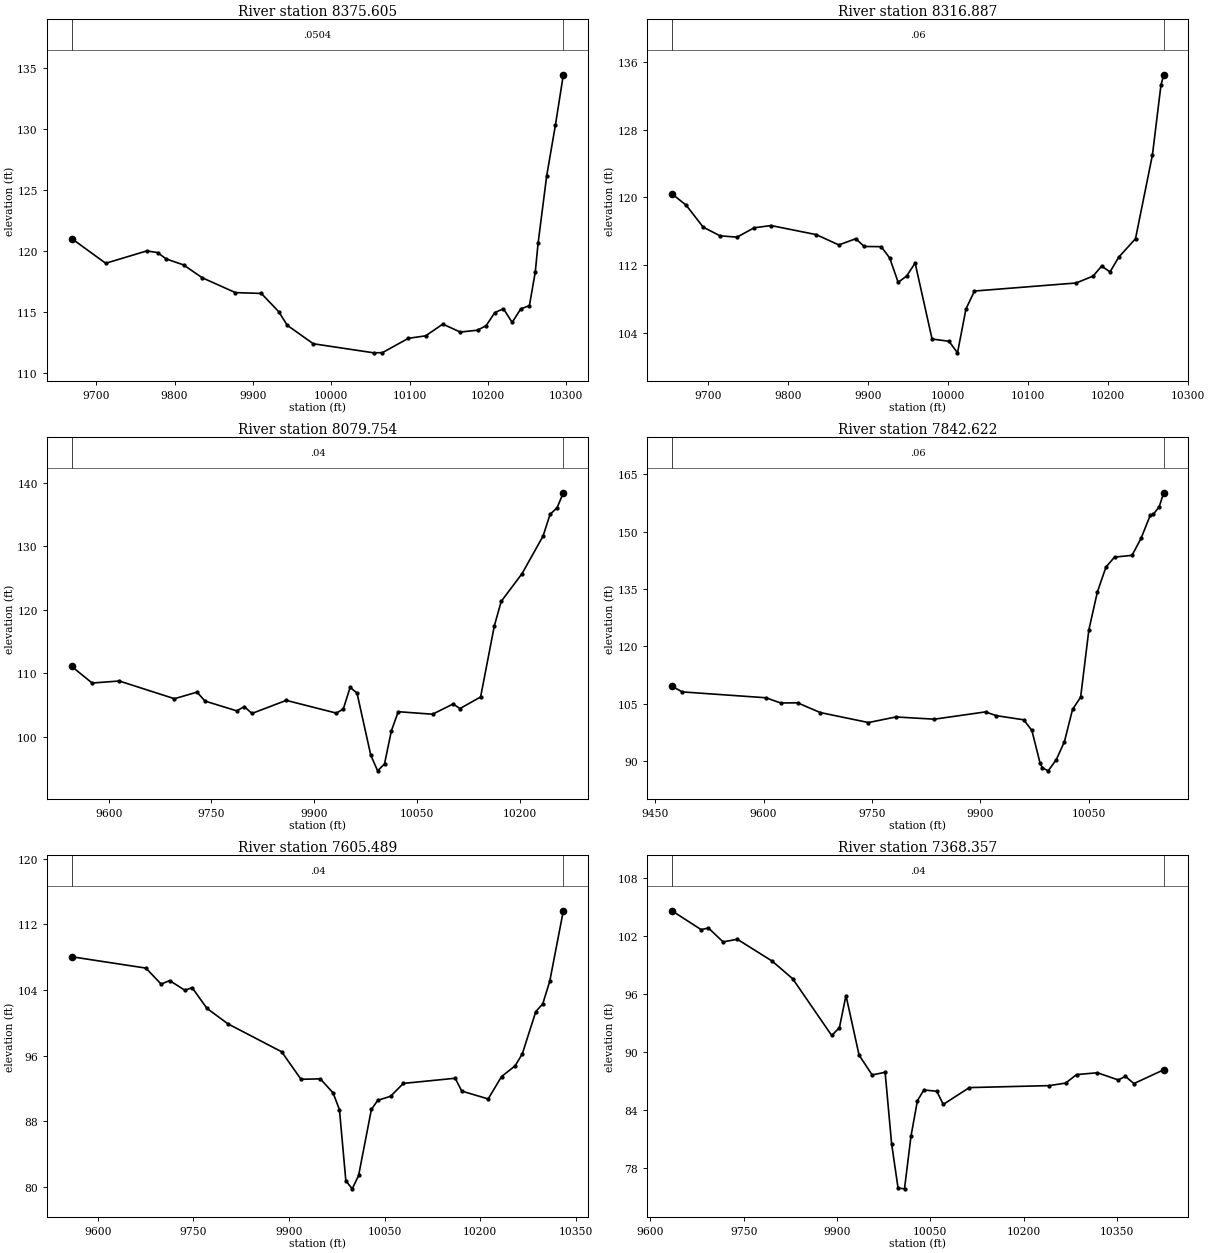
Type RM Length L Ch R = 1 ,8375.605,58.718600,58.718600,58.718600
XS GIS Cut Line= 2
829684.343320762719304.491202378829950.155226283718735.780928295
#Sta/Elev= 30
9668.488121.0402 9712.08 119.0119764.507120.02269778.311119.88769789.349119.3635
9811.426118.87859835.357117.82179877.656116.60759910.771116.53839932.848115.0502
9943.886113.92729977.058112.416510054.27111.672110065.31111.687310098.42112.8619
 10120.5113.064910142.38114.027210164.65113.375610186.73113.526910197.77113.9039
10208.81114.973310219.85 115.28510230.88114.165710241.92115.271110252.96 115.545
10260.46118.3065   10264120.642510275.04126.191510286.08 130.30910296.25134.4555
#Mann= 3 , 0 , 0
9668.488  0.0504       09668.488  0.0504       010296.25  0.0504       0
#XS Ineff= 2 , 0
       09963.173        10064.03       0
Bank Sta=9668.488,10296.25
Exp/Cntr=0.3,0.1

Type RM Length L Ch R = 1 ,8316.887,237.132400,237.132400,237.132400
XS GIS Cut Line= 2
829765.762465521719351.909557454829967.605574271718771.739107307
#Sta/Elev= 30
9655.073120.43629672.977119.07579694.152116.49869715.328115.47049736.504115.3227
 9757.68  116.429778.856116.68849835.353115.61699863.559114.40039884.735115.1322
9895.322114.21679916.498114.19659927.086112.86269937.674  109.999948.262110.7292
 9958.85112.26689980.026103.3011 10001.2103.034310011.79101.671910022.38106.8521
10032.97108.962910160.02109.9128 10181.2110.727210191.78 111.90310202.37  111.22
10212.96112.930810234.14115.138410255.31125.0287 10265.9133.230610269.35134.4731
#Mann= 3 , 0 , 0
9655.073    0.06       09655.073    0.06       010269.35    0.06       0
#XS Ineff= 2 , 0
       09963.233        10027.16       0
Bank Sta=9655.073,10269.35
Exp/Cntr=0.3,0.1

Type RM Length L Ch R = 1 ,8079.754,237.132300,237.132300,237.132300
XS GIS Cut Line= 6
829939.941827237719437.726262758830053.367851911719297.040542096
830109.980679304719177.712900361830118.089602872 719087.52733315
830108.908407724718924.695567452830132.838587012718776.286399823
#Sta/Elev= 30
9545.687111.11229575.704108.47879615.328108.79759695.904106.0091  9728.9107.0426
9740.626 105.6339786.828104.09869797.953104.76889809.078 103.6879859.175105.7459
9932.496103.73829942.497104.39789952.506  107.819962.538106.87899982.60197.11499
9992.632 94.652510002.67 95.7393 10012.7100.957410022.74103.963510072.85103.5685
10102.85105.180510112.86104.453710142.98106.282410163.06117.4905 10173.1121.3344
10203.63125.722610234.22131.626310244.42135.030210254.71136.0845 10263.8138.4328
#Mann= 3 , 0 , 0
9545.687    0.04       09545.687    0.04       0 10263.8    0.04       0
#XS Ineff= 2 , 0
       0                               0
Bank Sta=9545.687,10263.8
Exp/Cntr=0.3,0.1

Type RM Length L Ch R = 1 ,7842.622,237.132400,237.132400,237.132400
XS GIS Cut Line= 6
829955.235785156719453.997087704830094.317673774719307.308445039
830253.694347888719121.647687001830283.647464855719097.669638231
830406.015109585719029.493328314830449.934319685718996.318452875
#Sta/Elev= 30
9473.178109.63199487.242108.12889603.208106.59439623.666105.23149647.077105.2727
 9678.41 102.7369745.217100.12249783.126101.58419836.266101.00129907.179102.9058
9921.812101.93279960.015100.83489971.29698.072859982.57789.588569985.86488.31835
9993.85787.5155610005.1290.4298610016.3595.1269210027.57103.5414 10038.8106.7667
10050.22124.377710062.04134.264610073.85140.719810085.67143.309510109.95143.7788
10122.48 148.25810135.01154.188710139.33154.470710147.54 156.47410153.73160.1115
#Mann= 3 , 0 , 0
9473.178    0.06       09473.178    0.06       010153.73    0.06       0
#XS Ineff= 2 , 0
       0                               0
Bank Sta=9473.178,10153.73
Exp/Cntr=0.3,0.1

Type RM Length L Ch R = 1 ,7605.489,237.132400,237.132400,237.132400
XS GIS Cut Line= 6
829984.811104754719485.461486409830116.451428837719381.559446183
830208.442521043719334.914298825830315.569760742719311.418174485
830490.149605887719295.469810683830694.525274427719228.873141362
#Sta/Elev= 30
9558.614108.0434 9675.34106.66039699.216104.70929712.673105.13789736.388103.9656
9747.979104.27589771.162101.75439804.13399.872329888.48896.468069918.85293.11924
9949.12693.172889969.17891.465619979.20489.42184 9989.2380.767129999.25679.77682
10009.2881.4032410029.3389.4447110039.3590.5586610059.4391.04946 10079.692.61809
10160.9693.2454610171.1991.6829910212.6890.7265910233.7693.4550210254.9894.75345
10266.2896.2180310287.47101.363510298.41102.312310309.35105.047910330.71113.6416
#Mann= 3 , 0 , 0
9558.614    0.04       09558.614    0.04       010330.71    0.04       0
#XS Ineff= 2 , 0
       0                               0
Bank Sta=9558.614,10330.71
Exp/Cntr=0.3,0.1

Type RM Length L Ch R = 1 ,7368.357,237.132300,237.132300,237.132300
XS GIS Cut Line= 6
830065.134267576719691.656506637830145.082777804719642.110781419
830221.642503497719603.590151774830286.499463574719577.238304057
830592.676212335719479.629563333830788.273788774719380.917642745
#Sta/Elev= 30
9634.533104.57789681.538102.63089693.279102.80019716.761101.3682  9739.7101.6371
9795.67399.386759828.72197.563379891.38891.71046 9903.8192.514889914.35195.83596
9935.43289.680249956.48687.636569977.28587.918599987.68480.560559998.08375.96734
10008.4575.8895110018.8381.3064410029.2184.9824910039.5986.0927710060.3685.95621
10070.7884.5998310112.6686.3353810241.0786.5389110267.5586.80116   1028587.67625
10318.5887.8661110352.1687.12191 10363.587.4936710377.28 86.749910425.1488.17338
#Mann= 3 , 0 , 0
9634.533    0.04       09634.533    0.04       010425.14    0.04       0
#XS Ineff= 2 , 0
       0                               0
Bank Sta=9634.533,10425.14
Exp/Cntr=0.3,0.1

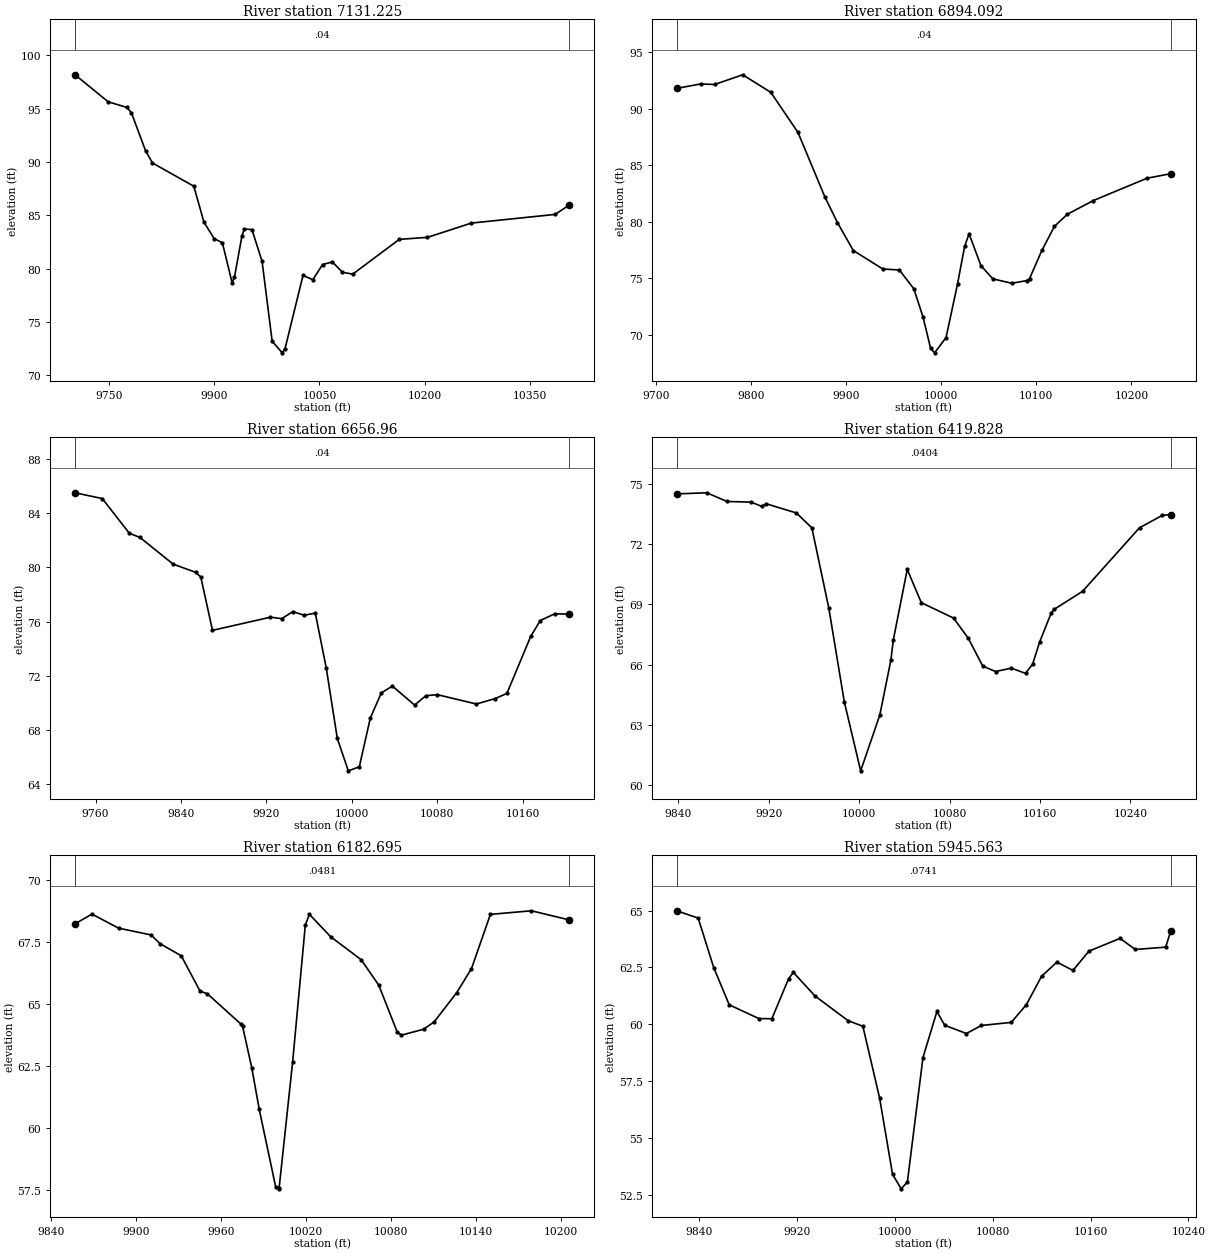
Type RM Length L Ch R = 1 ,7131.225,237.132400,237.132400,237.132400
XS GIS Cut Line= 6
830299.341984621719947.753239013830399.730305174719859.600504252
 830471.50985116719791.125667487830572.862005605719686.821444454
830639.660966288719626.064160152830827.227188264719482.922758263
#Sta/Elev= 30
9701.72698.177659748.86295.646029775.57895.115789781.93594.628969802.29491.04456
9812.10189.908479870.96887.730679885.456 84.36289899.94382.821739911.71382.42967
9925.53478.684869928.91879.181049939.54883.055079943.05883.726629953.92283.65973
9968.29680.686279982.67173.196889997.04572.11087   1000172.4922810026.6479.37264
10040.6178.9668810054.5780.3917210068.5480.6300210082.8679.6618410097.5479.48935
10163.96 82.749710204.0882.9372510266.5784.2745510385.9185.0870210406.2585.96981
#Mann= 3 , 0 , 0
9701.726    0.04       09701.726    0.04       010406.25    0.04       0
#XS Ineff= 2 , 0
       09951.072                       0
Bank Sta=9701.726,10406.25
Exp/Cntr=0.3,0.1

Type RM Length L Ch R = 1 ,6894.092,237.132400,237.132400,237.132400
XS GIS Cut Line= 6
830521.636850834720081.600987289830639.037812448719970.660954488
830695.100034071 719902.96052083830725.831349693719857.543120025
830782.145349477719786.795318564830869.446862462719697.534383007
#Sta/Elev= 30
 9721.7991.786119746.937 92.1763 9761.7392.131219791.31592.987739820.86991.43511
9849.39387.902369877.606 82.21799890.91979.933159907.59777.470159938.68675.83638
9956.04275.750489971.32474.080189980.96171.576099988.88668.833639993.068 68.4351
10005.1269.7845110017.1874.5064510024.6777.8440510029.3478.9409510041.8576.12784
10054.3574.9649910074.2274.5785710089.84 74.811210092.9174.9880810105.9377.48087
10119.0579.5989610132.6380.6687510159.7881.87307 10216.583.8550910241.5284.25415
#Mann= 3 , 0 , 0
 9721.79    0.04       0 9721.79    0.04       010241.52    0.04       0
#XS Ineff= 2 , 0
       09951.111        10026.15       0
Bank Sta=9721.79,10241.52
Exp/Cntr=0.3,0.1

Type RM Length L Ch R = 1 , 6656.96,237.132400,237.132400,237.132400
XS GIS Cut Line= 6
830613.407736762 720171.99275311830716.149482867720112.040611978
830771.381137466720088.192296464830901.412781556720052.545390574
830959.341476045 720031.43185339831036.832019026719991.900353897
#Sta/Elev= 30
9740.866 85.50579766.35585.07747 9791.6682.516989801.69582.206329832.69380.23572
9853.67279.638269858.57379.291059869.52175.348869923.84276.320449934.34676.21211
 9944.8576.732789955.35476.462459965.78576.623259976.08272.559379986.37967.37421
9996.67764.9760910006.9965.2731110017.32 68.880210027.6570.7360210037.98 71.2331
10058.7569.8311910069.3970.5255110080.0370.6000610116.5969.9108610134.0470.30596
10145.1870.6913910167.4874.9018310176.4476.0734910189.8876.5698310203.6276.54439
#Mann= 3 , 0 , 0
9740.866    0.04       09740.866    0.04       010203.62    0.04       0
#XS Ineff= 2 , 0
       0                10039.08       0
Bank Sta=9740.866,10203.62
Exp/Cntr=0.3,0.1

Type RM Length L Ch R = 1 ,6419.828,237.132300,237.132300,237.132300
XS GIS Cut Line= 6
830804.620372033 720393.80672617830873.693955943  720335.2748177
 830904.70419057720306.245714065830962.964608922720246.424710907
 831002.42945285720213.858681593 831136.94946103 720110.37824957
#Sta/Elev= 30
9838.35674.496659865.069 74.55159882.915 74.11919904.39174.084969913.85173.87087
9917.49974.006919944.38173.546719958.07972.804819973.07668.808129986.75364.15383
10001.2660.7123610018.1863.4859410027.9866.2129410030.1367.2168710042.4970.73484
10054.93 69.0836 10083.568.3141910096.4667.3137410109.34 65.925510120.6365.65545
10134.5665.8231510147.1765.5635710153.4566.0244810159.7867.1394710169.8668.56096
 10172.468.7450710197.62 69.645310248.0772.8106410268.33 73.429910275.81 73.4696
#Mann= 3 , 0 , 0
9838.356  0.0404       09838.356  0.0404       010275.81  0.0404       0
#XS Ineff= 2 , 0
       0                10062.25       0
Bank Sta=9838.356,10275.81
Exp/Cntr=0.3,0.1

Type RM Length L Ch R = 1 ,6182.695,237.132400,237.132400,237.132400
XS GIS Cut Line= 6
831023.520792044720533.528437997831083.784130586 720469.17886204
831100.904172276720446.148618175831134.523729344720392.323954172
831155.022868361720364.640955412831242.767566338720263.345555715
#Sta/Elev= 30
9856.956 68.22749868.88868.619319887.66768.053169910.648 67.77899916.81867.43191
9931.89866.939539945.14565.518599950.35265.407959973.84164.197789975.18664.09561
9981.70962.417599986.89860.76198 9998.6157.6109910000.7357.55067   1000157.59646
 10010.562.6559610019.4568.1740510022.3268.6116510037.31 67.708610058.8666.78283
10071.3165.7557410084.3263.8681510087.3163.74231 10102.963.9804710110.3964.27607
10126.3565.4570610136.7166.4219610150.0968.6082310179.0268.7530510205.7868.38452
#Mann= 3 , 0 , 0
9856.956  0.0481       09856.956  0.0481       010205.78  0.0481       0
#XS Ineff= 2 , 0
       0                10025.59       0
Bank Sta=9856.956,10205.78
Exp/Cntr=0.3,0.1

Type RM Length L Ch R = 1 ,5945.563,86.831300,86.831300,86.831300
XS GIS Cut Line= 6
  831101.1253462720721.339071348831134.982525583720694.799059495
 831313.24301253720572.596058341831352.188298951720544.183723521
831384.338942313  720517.0195082831428.419724182720484.502837198
#Sta/Elev= 30
9821.47964.987919839.10864.668349851.81562.49259 9864.5260.852559888.80860.24648
9899.39360.241649913.09662.004779917.01862.277159934.64261.241399961.67260.15809
9973.81659.908079987.51656.747579998.10553.3937910005.1652.7596610010.2253.06445
10022.9658.5330910034.3960.5615610040.7559.9502310058.5559.5907110070.6659.94412
10095.1860.0791610107.5660.8604510119.9462.1059110132.5162.7304210145.6162.36493
 10158.763.2122910184.1763.77442 10196.663.2861710221.4563.38903 10225.764.10982
#Mann= 3 , 0 , 0
9821.479  0.0741       09821.479  0.0741       0 10225.7  0.0741       0
#XS Ineff= 2 , 0
       09933.777        10034.86       0
Bank Sta=9821.479,10225.7
Exp/Cntr=0.3,0.1