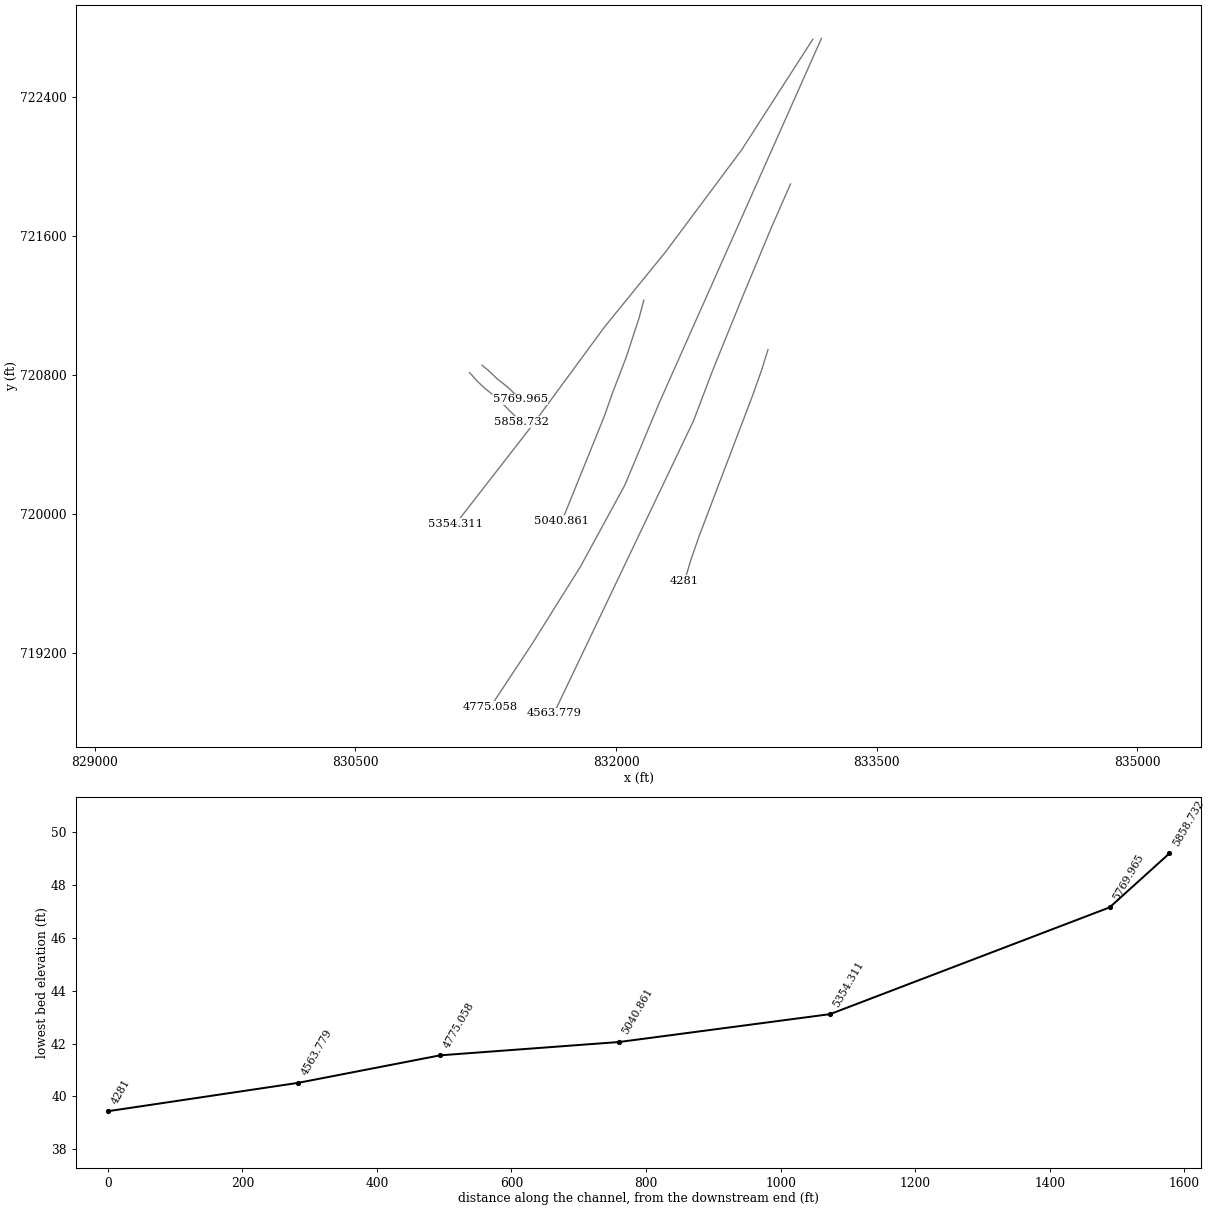
HEC-RAS study 7731_ras.prj: 7731

--- 7731_ras.g01 (geometry) --- (continued)

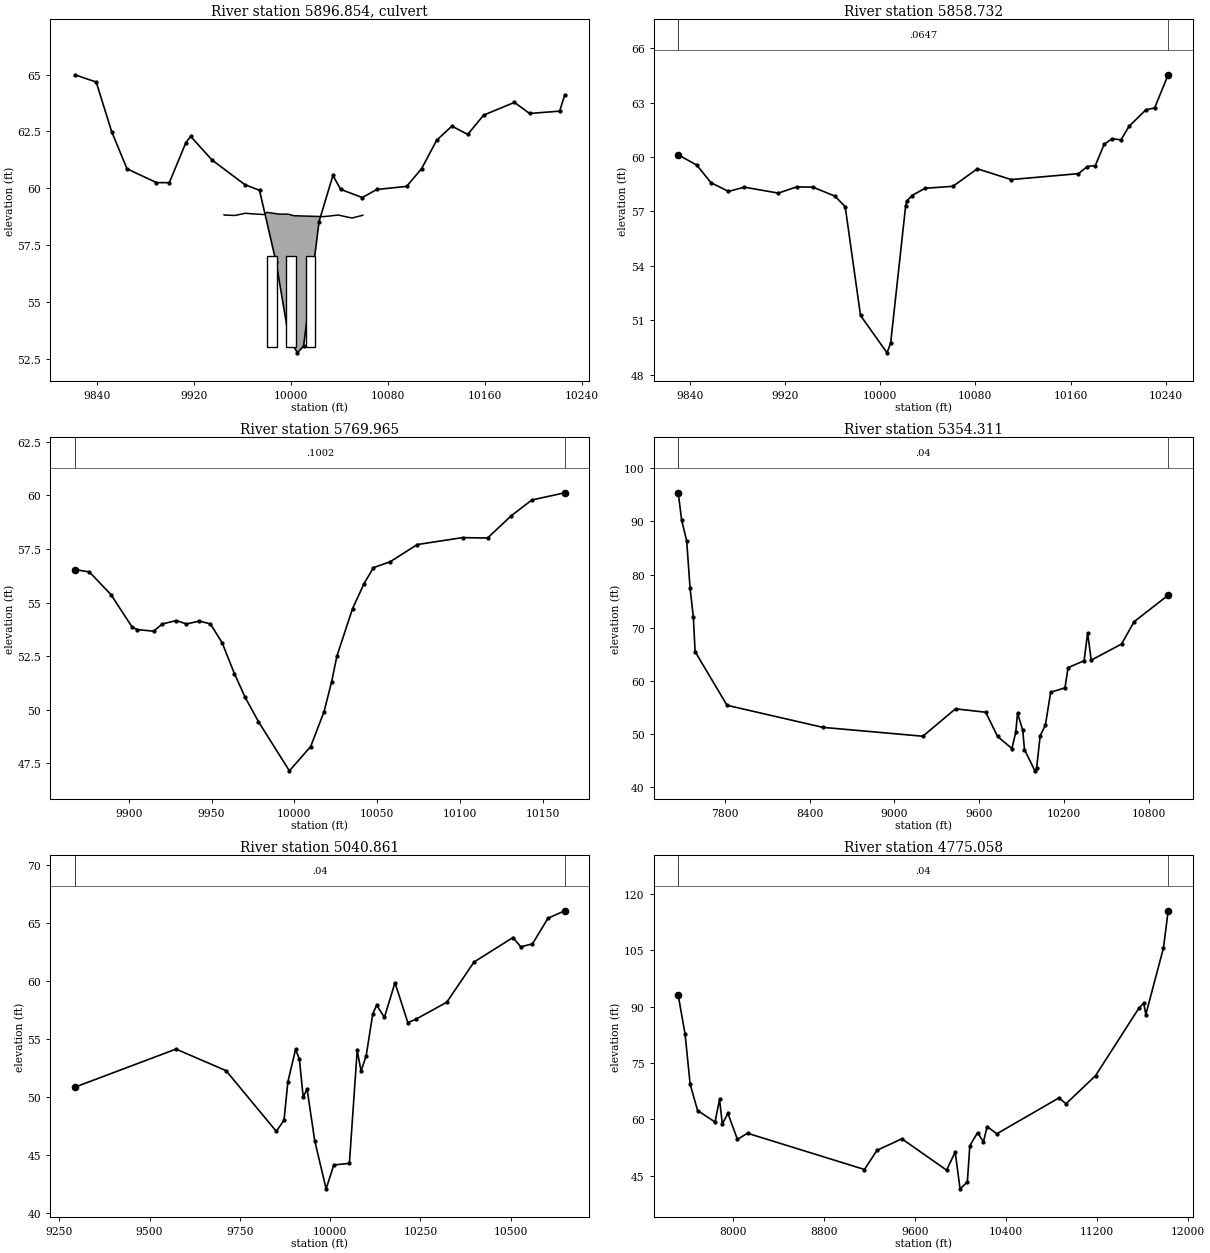
Type RM Length L Ch R = 2 ,5896.854,,,
Bridge Culvert--1,0,-1,-1, 0
Deck Dist Width WeirC Skew NumUp NumDn MinLoCord MaxHiCord MaxSubmerge Is_Ogee
30.416,26,2.6,0,18,18, , , 0.95, 0, 0,0,,
 9944.57 9944.85 9953.44 9962.35 9965.62 9977.80 9979.86 9989.99 9997.3710002.17
10014.3510014.8810026.5410032.3810038.7210049.8910050.9010059.08
   58.83   58.82   58.80   58.90   58.88   58.84   58.94   58.86   58.86   58.79
   58.77   58.77   58.75   58.78   58.82   58.69   58.70   58.81
                                                                                
                                                                
 9944.57 9944.85 9953.44 9962.35 9965.62 9977.80 9979.86 9989.99 9997.3710002.17
10014.3510014.8810026.5410032.3810038.7210049.8910050.9010059.08
   58.83   58.82   58.80   58.90   58.88   58.84   58.94   58.86   58.86   58.79
   58.77   58.77   58.75   58.78   58.82   58.69   58.70   58.81
                                                                                
                                                                
BR Coef=-1 , 0 , 0 ,, 0 ,,,0.8,-1,,0,
WSPro=,,,, 1 ,,,, 0 ,,,, 0 ,,,,-1 ,-1 ,-1 , 0 , 0 , 0 , 0 , 0
Multiple Barrel Culv=2,4,8,26,0.013,0.5,1,8,3,53,50,3,Culvert #1, 0, 30.416
 9984.00 9984.0010000.0010000.0010016.0010016.00
Culvert Bottom n=0.013
BC Design=,, 0 ,, 0 ,,,,,,

Type RM Length L Ch R = 1 ,5858.732,88.767100,88.767100,88.767100
XS GIS Cut Line= 6
831156.737665561720816.664764937831197.045069855720771.006793175
831248.298953956720722.188137888831299.133993064 720682.32789691
831325.236010903720659.296925405831453.063288932720531.766122058
#Sta/Elev= 30
9830.31360.126629845.87359.561349857.90758.587059872.55158.107989885.89158.34142
9914.42658.014339929.82458.355599943.42458.34457    996257.847629970.61757.26816
9983.47651.2645310005.7849.20132 10008.849.73936 10021.457.3069510022.2257.55499
10026.6157.8768710037.6958.2801710061.1158.3892610081.66 59.356610109.9858.76116
10166.6159.0879610174.0959.4821510180.7759.5335610188.2260.7071310194.9361.01903
10202.3460.9511910209.0961.6986710223.2562.60711 10230.662.7150710241.9964.54269
#Mann= 3 , 0 , 0
9830.313  0.0647       09830.313  0.0647       010241.99  0.0647       0
#XS Ineff= 2 , 0
       0 9957.29        10046.47       0
Bank Sta=9830.313,10241.99
Exp/Cntr=0.3,0.1

Type RM Length L Ch R = 1 ,5769.965,415.653800,415.653800,415.653800
XS GIS Cut Line= 6
831228.236016388720858.846328985831265.014017413720828.648819693
831316.267907506 720779.83026283831367.102943395720739.970111843
831393.204962329720716.939188848831449.262402216720662.466191015
#Sta/Elev= 30
9867.41656.534989876.16856.426569889.23655.368479902.04653.852579904.99453.74144
9914.98553.663249920.29354.004139928.794 54.15939934.79354.002029942.60454.13396
9949.29254.005989956.41453.120099963.79151.690429970.22550.59259 9978.2949.45264
9997.01447.1579410009.8748.2915910017.96  49.91910022.5551.3180310025.6952.49971
10035.1554.7151110042.1355.8854810047.7556.6239410057.9156.9001710074.2657.70224
10101.6558.0242110116.6958.0048310131.0459.0431210143.4859.7780910163.3760.11331
#Mann= 3 , 0 , 0
9867.416  0.1002       09867.416  0.1002       010163.37  0.1002       0
#XS Ineff= 2 , 0
       09956.222                       0
Bank Sta=9867.416,10163.37
Exp/Cntr=0.3,0.1

Type RM Length L Ch R = 1 ,5354.311,313.449700,313.449700,313.449700
XS GIS Cut Line= 6
833133.038752958722735.471471413832723.574627726722099.061534286
832283.086131642721508.418812729831934.561911436721079.931374606
831513.097562523720506.663050041831077.111246878719945.880551939
#Sta/Elev= 30
7470.08895.37214 7494.4390.224417530.103 86.31377553.88577.495967577.35371.95485
7589.55865.528237815.48755.433298493.87951.284979201.38349.617169432.78754.77073
9646.48154.12602 9730.0549.587129831.79247.308819859.36450.379729871.67553.96302
9908.60950.74734 9920.9247.109929994.78743.1143810007.1543.6667610031.8749.69976
10068.9551.7137410106.0357.8771710207.3358.7169110229.6762.5104610342.8763.80829
10368.0269.0394910393.1863.9151310607.7166.9434810696.9271.1431310937.9376.12376
#Mann= 3 , 0 , 0
7470.088    0.04       07470.088    0.04       010937.93    0.04       0
#XS Ineff= 2 , 0
       09892.587        10048.58       0
Bank Sta=7470.088,10937.93
Exp/Cntr=0.3,0.1

Type RM Length L Ch R = 1 ,5040.861,265.803100,265.803100,265.803100
XS GIS Cut Line= 6
832160.008451266721233.410876392832131.550880714721126.345606713
832058.340728773720904.157821404831978.274679256720695.132227564
 831932.05810029720563.638261037831688.575549528719961.861824399
#Sta/Elev= 30
9293.01550.836679573.26154.124679711.83352.261059851.04447.020969872.38847.98593
9883.024 51.28639904.29554.090269914.93153.274859925.56749.954299936.20350.69333
9957.37346.22241 9989.0242.0598710010.3244.1244910053.4744.2577710075.0454.00588
10085.8352.24071 10099.853.5171710118.1957.1619710128.9857.9138510150.5656.86613
10179.7959.8538810215.2856.4165510236.8656.6877210323.1658.1691310398.6761.63804
10506.5463.7556110528.1262.9535910560.4863.2060810603.6365.4211110650.1766.06395
#Mann= 3 , 0 , 0
9293.015    0.04       09293.015    0.04       010650.17    0.04       0
#XS Ineff= 2 , 0
       0 9902.43        10083.69       0
Bank Sta=9293.015,10650.17
Exp/Cntr=0.3,0.1

Type RM Length L Ch R = 1 ,4775.058,211.279100,211.279100,211.279100
XS GIS Cut Line= 6
833182.570482824722740.533835849832249.807404173  720644.2090592
832050.458350768720167.985466179 831794.99748098719698.938891065
831515.612938378719252.572354165831276.365404772718890.759532922
#Sta/Elev= 30
7517.71993.004037578.50282.615037622.28369.397287687.95562.375937841.18859.30813
7880.72465.329747905.322 58.8189 7954.5261.601768038.20254.701878126.71156.33148
9154.61646.694879264.06951.791749482.97454.852929876.18646.524859951.56351.33229
  9994.441.5555910058.7143.3779910080.1653.0119710148.64 56.499210199.6654.04761
10232.7358.0894710317.8456.1947610862.88 65.7122 10926.164.1781411184.99  71.631
11566.27 89.597211608.6190.9117111626.7787.89309   11782105.590811823.27115.4615
#Mann= 3 , 0 , 0
7517.719    0.04       07517.719    0.04       011823.27    0.04       0
#XS Ineff= 2 , 0
       09931.312        10090.18       0
Bank Sta=7517.719,11823.27
Exp/Cntr=0.3,0.1

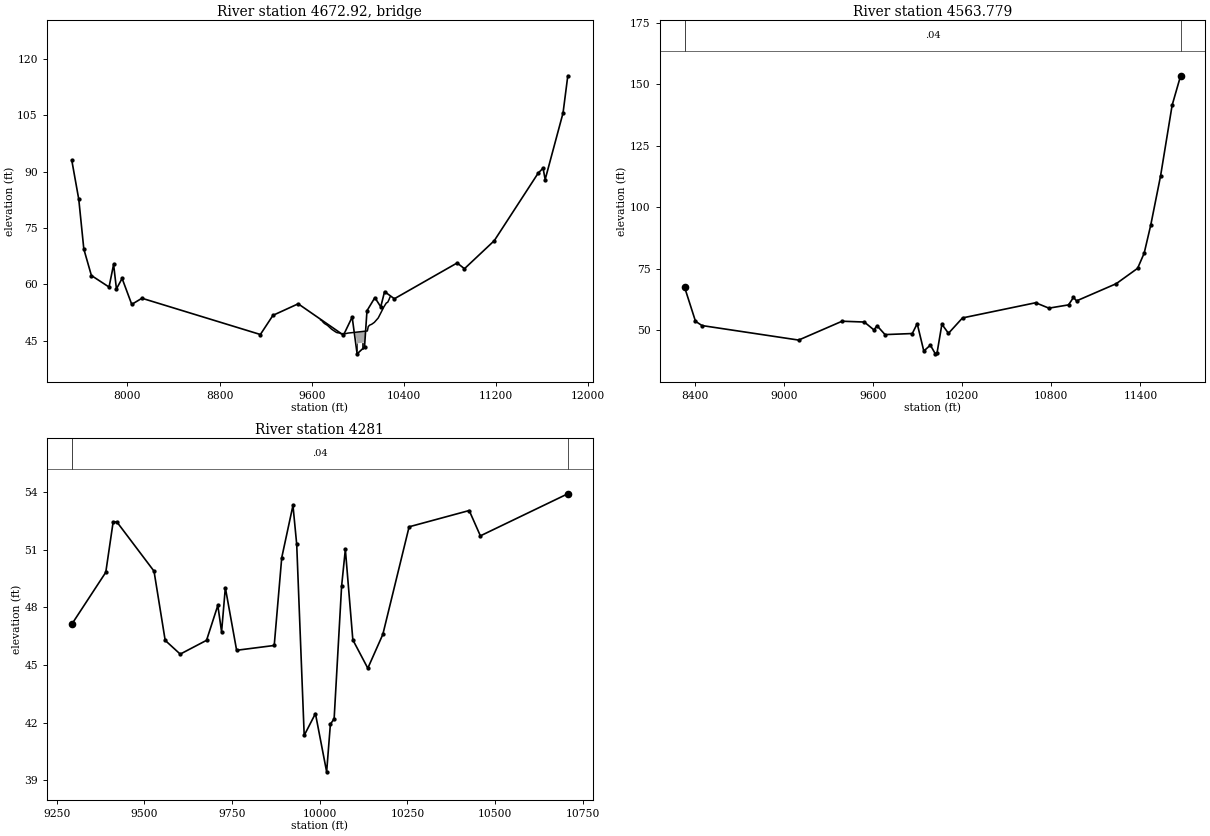
Type RM Length L Ch R = 3 , 4672.92,,,
BEGIN DESCRIPTION:
END DESCRIPTION:
Bridge Culvert--1,0,-1,-1, 0
Deck Dist Width WeirC Skew NumUp NumDn MinLoCord MaxHiCord MaxSubmerge Is_Ogee
94.639550,22.000000,2.6,0, 28, 29, , , 0.95, 0, 0,0,,
 9678.30 9686.18 9701.72 9713.53 9737.14 9772.56 9807.97 9819.78 9843.39 9855.19
 9878.80 9890.61 9914.38 9942.03 9942.0310083.4810091.0310091.0310102.2910121.05
10144.0110177.7010226.8910247.6210260.2310272.8510276.0810282.04
   50.57   50.46   49.88   49.57   49.13   48.12   47.38   47.19   47.08   46.90
   46.95   46.89   47.07   47.16   47.16   47.64   48.79   48.79   49.17   49.42
   49.92   51.09   54.04   55.06   55.27   56.07   56.37   56.74
 -949.43 -949.54 -950.12 -950.43 -950.87 -951.88 -952.62 -952.81 -952.92 -953.10
 -953.05 -953.11 -952.93 -952.84   44.16   44.64   45.79 -951.21 -950.83 -950.58
 -950.08 -948.91 -945.96 -944.94 -944.73 -943.93 -943.63 -943.26
 9678.30 9686.18 9701.72 9713.53 9737.14 9772.56 9807.97 9819.78 9843.39 9855.19
 9878.80 9890.61 9907.83 9907.8310056.8310056.8310083.4810091.1810102.2910121.05
10144.0110171.9110184.5310226.8910247.6210260.2310272.8510276.0810282.04
   50.57   50.46   49.88   49.57   49.13   48.12   47.38   47.19   47.08   46.90
   46.95   46.89   47.01   47.01   47.55   47.55   47.64   48.81   49.17   49.42
   49.92   50.85   51.45   54.04   55.06   55.27   56.07   56.37   56.74
 -949.43 -949.54 -950.12 -950.43 -950.87 -951.88 -952.62 -952.81 -952.92 -953.10
 -953.05 -953.11 -952.99   44.01   44.55 -952.45 -952.36 -951.19 -950.83 -950.58
 -950.08 -949.15 -948.55 -945.96 -944.94 -944.73 -943.93 -943.63 -943.26
Pier Skew, UpSta & Num, DnSta & Num=  ,9991.20, 2 ,9957.00, 2 , 0 , 0 , 0 ,,
    3.00    3.00
 -952.68   47.32
    3.00    3.00
 -952.79   47.21
Pier Skew, UpSta & Num, DnSta & Num=  ,10041.86, 2 ,10007.66, 2 , 0 , 0 , 0 ,,
    3.00    3.00
 -952.50   47.50
    3.00    3.00
 -952.62   47.38
BR Coef=-1 , 0 , 0 ,, 0 ,,,0.8,0,1,0,
WSPro=,,,, 1 ,,,, 0 ,,,, 0 ,,,,-1 ,-1 ,-1 , 0 , 0 , 0 , 0 , 0
BC Design=,, 0 ,, 0 ,,,,,,

Type RM Length L Ch R = 1 ,4563.779,282.778800,282.778800,282.778800
XS GIS Cut Line= 6
833004.550075065721902.179939964832897.794353041721659.332570173
832729.740641934721256.130525655832557.416491993720831.537133881
832445.920253535720538.343520052831642.292892531718854.453523053
#Sta/Elev= 30
8330.67667.559288404.06153.735618447.75551.998899098.56346.102689391.06653.75898
9540.935 53.4291 9605.3150.241289626.76851.915089680.41348.32814  9863.848.75716
9897.03352.765429941.34341.648829985.65344.0523610018.8940.5124210029.96 40.6511
 10063.252.5310710107.5148.8446110202.0155.0990810694.5461.2633410783.6259.06669
10915.9960.3965210949.2163.4340510969.9662.0189311237.0869.0012811381.0275.24415
11425.3181.40918 11469.6 92.826211536.04   112.911613.54141.484511670.63153.4405
#Mann= 3 , 0 , 0
8330.676    0.04       08330.676    0.04       011670.63    0.04       0
#XS Ineff= 2 , 0
       09905.125        10060.09       0
Bank Sta=8330.676,11670.63
Exp/Cntr=0.3,0.1

Type RM Length L Ch R = 1 ,    4281,0.000000,0.000000,0.000000
XS GIS Cut Line= 6
832874.670592594720947.460376839832837.570299956 720829.29850841
832789.822772757 720693.94508668832477.062638208719871.729773259
832429.645028536719734.351562439832394.877560353719617.858710632
#Sta/Elev= 30
9293.00747.124989389.91749.82843 9410.8852.445859421.41452.454679527.454 49.8881
9559.266 46.28429602.12845.56852 9677.1646.286759709.31648.104949720.03546.72832
9730.75349.02875 9762.9145.768369870.09746.01911  9891.550.588099923.52153.31147
9934.19551.283649955.54241.335979987.56342.4728610019.5439.4385810030.2141.92259
10040.8742.19781 10062.2   49.1110072.8651.0225310094.1946.3104310136.8844.83339
 10179.746.5957410254.6252.1980310425.8853.0453510457.7951.7268910706.9953.91764
#Mann= 3 , 0 , 0
9293.007    0.04       09293.007    0.04       010706.99    0.04       0
#XS Ineff= 2 , 0
       09918.614        10078.34       0
Bank Sta=9293.007,10706.99
Exp/Cntr=0.3,0.1